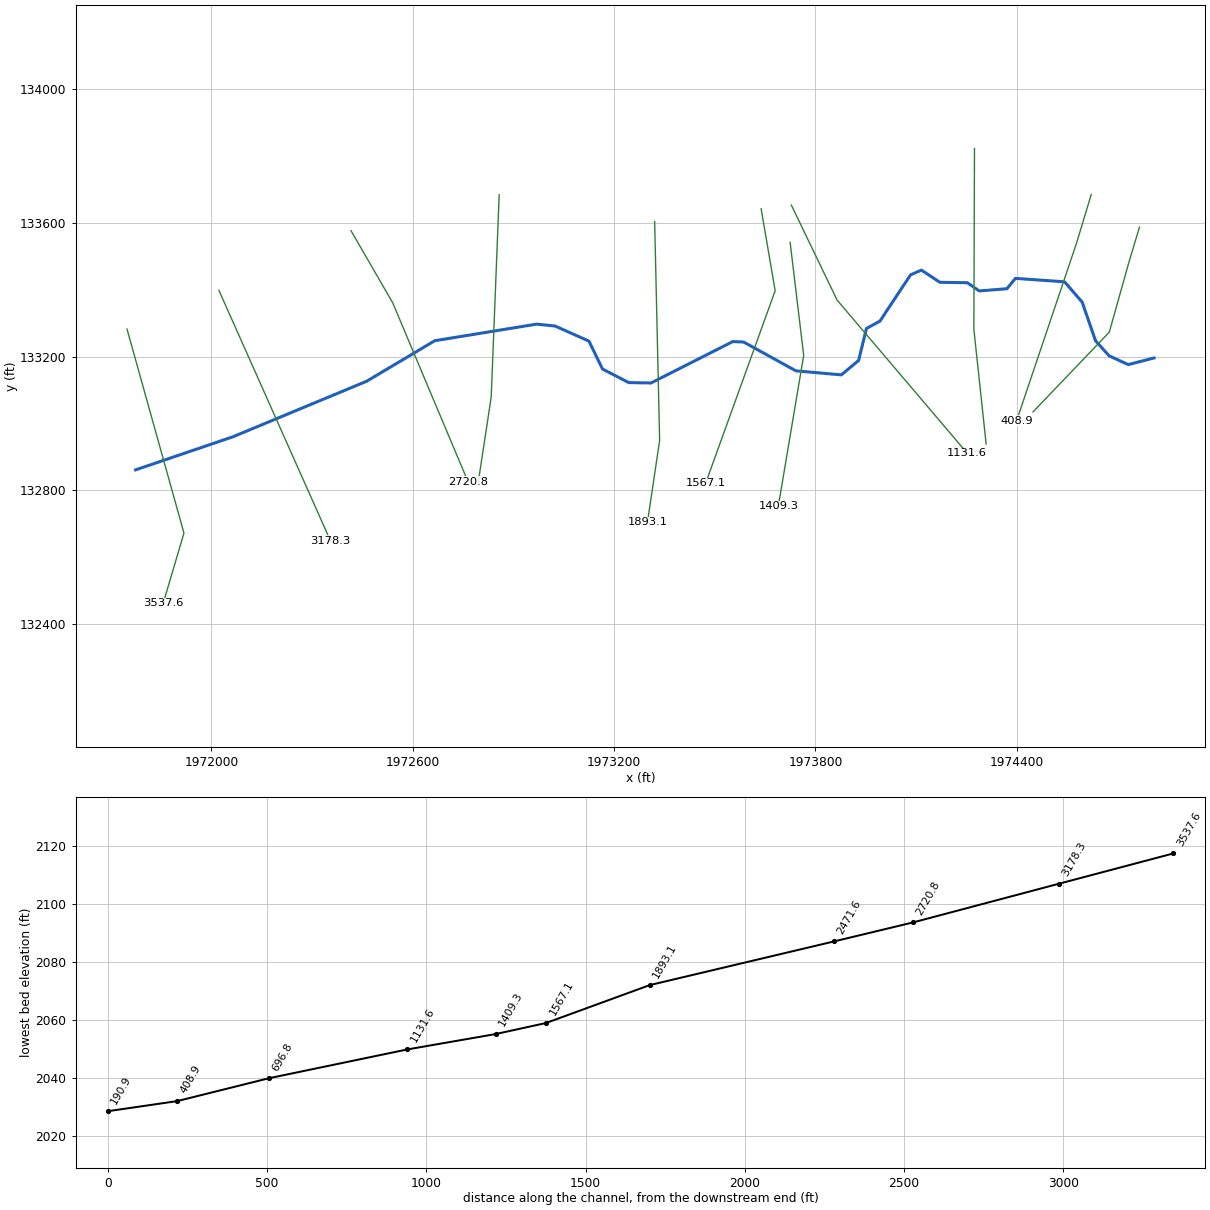
--- PynBrTrb.prj (project) ---

Proj Title=PynBrTrb
Current Plan=p01
Default Exp/Contr=0,0
English Units
Geom File=g01
Flow File=f01
Plan File=p01
BEGIN DESCRIPTION:
END DESCRIPTION:
DSS Export Rating Curves= 0
DSS Export Rating Curve Sorted= 0
DSS Export Volume Flow Curves= 0
DXF OffsetX= 0
DXF OffsetY= 0
DXF ScaleX= 0
DXF ScaleY= 0

--- PynBrTrb.p01 (plan) ---

Plan Title=Floodplain
Program Version=4.00
Geom File=g01
Flow File=f01
K Sum by GR=0
Std Step Tol=0.01
Critical Tol=0.01
Num of Std Step Trials=20
Max Error Tol=0.3
Flow Tol Ratio=0.001
Split Flow NTrial=30
Split Flow Tol=0.02
Split Flow Ratio=0.02
Log Output Level=0
Friction Slope Method=1
Unsteady Friction Slope Method=2
Unsteady Bridges Friction Slope Method=1
Global Log Level=0
CheckData=False
Run HTab=0
Run UNet=0
Run PostProcess=0
UNET Theta=0
UNET Theta Warmup=0
UNET ZTol=0
UNET ZSATol=0
UNET MxIter=0
UNET MaxInSteps=0
UNET DtIC=0
UNET DtMin=0
UNET MaxCRTS=0
UNET WFStab=0
UNET SFStab=0
UNET WFX=0
UNET SFX=0
UNET DSS MLevel=0
UNET DZMax Abort=0
UNET Convert EG Bridges=0
UNET Use Existing IB Tables=0
UNET Froude Limit=0
UNET Froude Power=0
Write IC File=0
Echo Input=False
Echo Output=False
Write Detailed=0

--- PynBrTrb.f01 (steady flow) ---

Flow Title=NFF Regression Equation
Program Version=4.00
Number of Profiles=1
Profile Names=P100yr
River Rch & RM=PynBrTrb,Main      ,3537.6
481.6342
River Rch & RM=PynBrTrb,Main      ,3178.3
584.3071
River Rch & RM=PynBrTrb,Main      ,2720.8
588.3161
River Rch & RM=PynBrTrb,Main      ,190.9
651.5766
Boundary for River Rch & Prof#=PynBrTrb,Main      ,1
Up Type=0
Dn Type=3
Dn Slope=0.021749

--- PynBrTrb.g01 (geometry) ---

Geom Title=USGS 3m DEM
Program Version=4.10

River Reach=PynBrTrb        ,Main
Reach XY= 30
     1971774.045      132861.636     1972064.122      132960.436
     1972462.423      133126.199     1972665.548      133247.293
     1972968.934      133296.772     1973023.776      133291.321
     1973125.184      133245.991     1973165.548      133162.657
     1973243.673      133122.293      1973310.08      133120.991
     1973553.569      133244.689     1973586.121      133243.386
      1973741.68      133157.372     1973877.464      133145.287
     1973928.862      133188.569     1973952.007      133283.751
     1973992.371      133305.886     1974083.517      133443.907
     1974116.069       133458.23     1974170.757      133421.772
     1974252.788       133420.47     1974288.246      133395.963
     1974370.936      133402.596     1974396.017      133433.491
     1974542.555      133423.234     1974594.932      133362.757
     1974634.902      133247.181     1974675.479      133202.095
     1974732.287      133175.945     1974809.277      133195.801

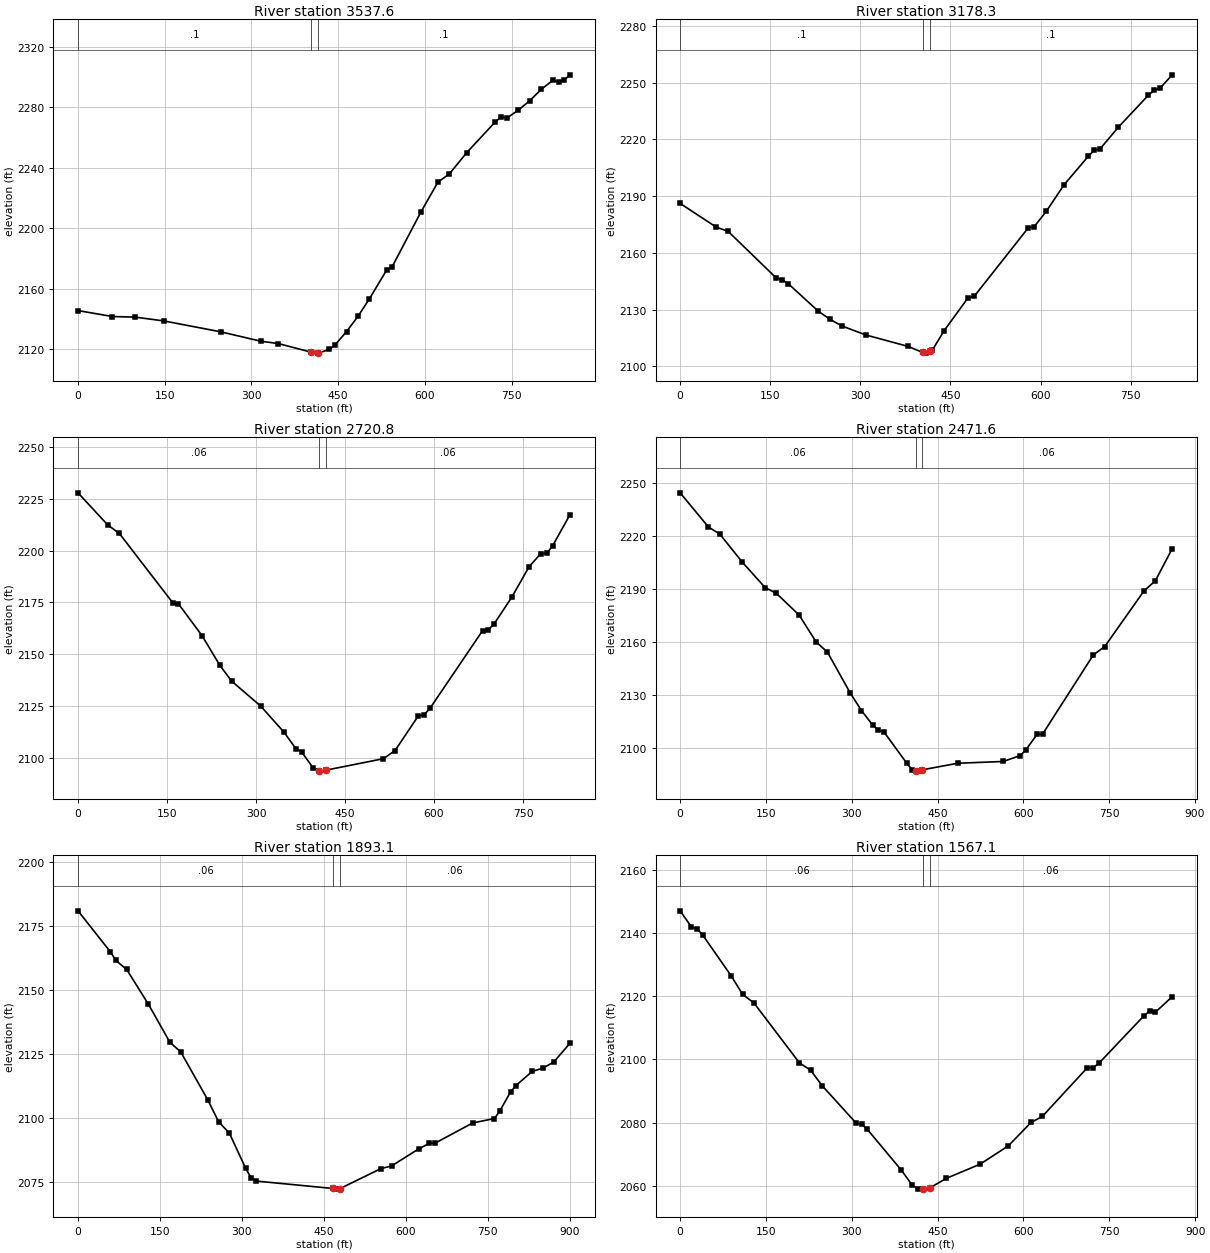
Type RM Length L Ch R = 1 ,3537.6  ,356.3,359.3,362.3
XS GIS Cut Line= 3
     1971748.394      133282.041     1971918.069       132672.76
     1971856.182      132463.137
#Sta/Elev= 30
       0 2145.53    59.3  2141.6    98.8 2141.18   148.2 2138.71   247.1 2131.46
   316.2 2125.26   345.9 2123.75     403 2118.07     415 2117.39   434.8 2119.84
   444.7 2122.85   464.5 2131.66   484.2 2141.69     504  2153.3   533.6 2172.17
   543.5 2174.61   592.9  2210.6   622.6 2230.51   642.4 2235.92   672.2 2249.92
   721.9  2270.4   731.8 2273.58   741.8 2272.87   761.6 2278.06   781.5 2284.38
   801.4 2291.85   821.2 2297.79   831.2 2296.69   841.1 2297.95     851 2301.43
#Mann= 3 , 0 , 0
       0      .1       0     403    .045       0     415      .1       0
Bank Sta=403,415
XS Rating Curve= 0 ,0
Exp/Cntr=0.3,0.1

Type RM Length L Ch R = 1 ,3178.3  ,457.8,457.4,456.9
XS GIS Cut Line= 3
     1972022.243      133397.761     1972188.559      133023.556
     1972354.874      132649.351
#Sta/Elev= 30
       0 2186.12    59.9 2173.62    79.9 2171.33   159.8 2146.74   169.8 2145.78
   179.8 2143.71   229.7  2129.2   249.7 2124.78   269.7 2121.25   309.6 2116.52
   379.5  2110.5   403.5 2107.36   409.5 2106.96   415.5 2107.84   419.5 2108.42
   439.5 2118.87   479.4 2136.28   489.4 2136.96   579.3 2173.14   589.3 2173.81
   609.3 2181.87   639.2 2196.03   679.2 2210.98   689.2 2214.24   699.2 2215.03
   729.1  2226.3     779 2243.21     789 2245.97     799 2247.08     819 2254.12
#Mann= 3 , 0 , 0
       0      .1       0   403.5    .045       0   415.5      .1       0
Bank Sta=403.5,415.5
XS Rating Curve= 0 ,0
Exp/Cntr=0.3,0.1

Type RM Length L Ch R = 1 ,2720.8  ,258.7,249.3,239.9
XS GIS Cut Line= 3
     1972415.862      133576.049     1972540.311      133360.338
     1972765.063      132825.384
#Sta/Elev= 30
       0 2227.82    49.8 2212.42    69.7 2208.22   159.4 2174.92   169.3 2174.31
   209.2  2158.9   239.1 2144.64   258.9 2137.06     308 2124.99   347.4 2112.36
     367 2104.56   376.9 2102.95   396.6 2095.07   405.9 2093.73   406.4 2093.66
   417.9 2094.13   514.6 2099.64   534.2 2103.51   573.6 2120.29   583.4 2120.82
   593.2 2123.91   681.8 2161.33   691.6 2161.85   701.4 2164.65   730.9  2177.4
   760.4 2192.23   780.1 2198.57     790 2198.63   799.8 2202.22   829.3 2217.32
#Mann= 3 , 0 , 0
       0     .06       0   405.9    .045       0   417.9     .06       0
Bank Sta=405.9,417.9
XS Rating Curve= 0 ,0
Exp/Cntr=0.3,0.1

Type RM Length L Ch R = 1 ,2471.6  ,578.1,578.2,578.5
XS GIS Cut Line= 3
     1972857.538      133682.912     1972833.802      133079.292
      1972795.43      132826.246
#Sta/Elev= 30
       0 2244.61    49.5 2225.25    69.3 2221.25   108.9 2205.26   148.6 2190.98
   168.4 2187.66     208 2175.38   237.7 2160.22   257.5 2154.41   297.1  2131.4
   316.9  2121.4   336.7 2113.08   346.6 2110.27   356.5 2109.14   396.1 2091.58
     406 2087.72   411.5 2087.37   415.9 2087.09   423.5 2087.84   485.2 2091.55
   564.5 2092.55   594.2 2095.86   604.1 2099.04   623.8 2107.86   633.6 2108.08
   722.2 2152.87   741.9 2157.51   810.8  2189.1   830.5 2194.78     860 2212.94
#Mann= 3 , 0 , 0
       0     .06       0   411.5    .045       0   423.5     .06       0
Bank Sta=411.5,423.5
XS Rating Curve= 0 ,0
Exp/Cntr=0.3,0.1

Type RM Length L Ch R = 1 ,1893.1  ,333.1,325.5,317.7
XS GIS Cut Line= 3
     1973320.901      133602.854     1973335.744      132949.658
     1973299.447      132704.909
#Sta/Elev= 30
       0 2180.82    59.4 2164.76    69.3 2161.43    89.1  2157.9   128.7 2144.39
   168.3 2129.42   188.1 2125.68   237.6 2106.94   257.4 2098.41   277.2  2093.9
   306.9  2080.2   316.8 2076.54   326.7  2075.2     467 2072.31   475.2 2072.06
     479  2072.2   554.4 2080.06   574.2 2081.13   623.7 2087.77   643.5 2089.99
   653.4 2089.99   722.6 2097.92   762.2 2099.64   772.1 2102.54   791.9 2110.06
   801.8 2112.54   831.5 2118.06   851.3 2119.35   871.1 2121.75   900.8 2129.09
#Mann= 3 , 0 , 0
       0     .06       0     467    .045       0     479     .06       0
Bank Sta=467,479
XS Rating Curve= 0 ,0
Exp/Cntr=0.3,0.1

Type RM Length L Ch R = 1 ,1567.1  ,153.9,157.7,161.4
XS GIS Cut Line= 3
     1973638.222      133641.119     1973680.052      133396.635
     1973472.637      132821.061
#Sta/Elev= 30
       0    2147    19.8 2141.87    29.8 2141.32    39.7 2139.28    89.3 2126.41
   109.1  2120.6     129 2117.87   208.4 2098.94   228.2 2096.57     248 2091.75
   307.2 2079.95   317.1 2079.55     327 2077.93   386.2  2065.1   405.9 2060.19
   415.8 2059.02   424.1 2059.05   436.1 2059.39   465.1 2062.42   524.3 2066.92
   573.7 2072.74   613.2  2080.1   632.9 2081.99   711.8 2097.46   721.7  2097.4
   731.6 2098.77   810.5 2113.82   820.4 2115.33   830.2 2114.92   859.8 2119.83
#Mann= 3 , 0 , 0
       0     .06       0   424.1    .045       0   436.1     .06       0
Bank Sta=424.1,436.1
XS Rating Curve= 0 ,0
Exp/Cntr=0.3,0.1

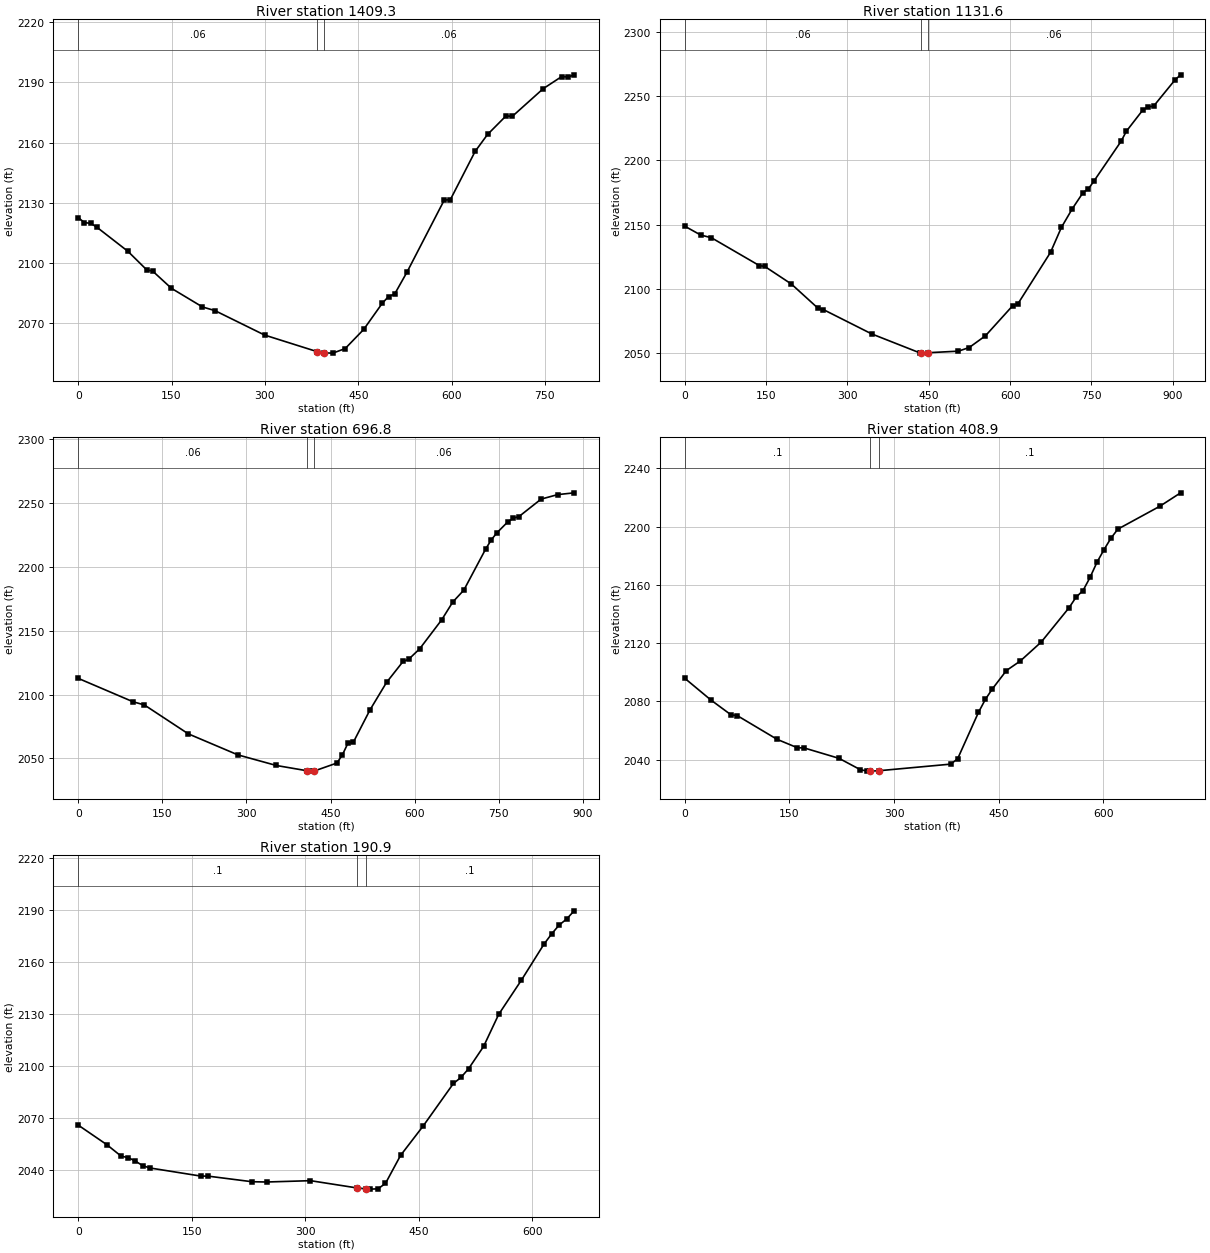
Type RM Length L Ch R = 1 ,1409.3  ,260,277.7,295.4
XS GIS Cut Line= 3
     1973724.646      133540.788     1973765.091       133203.74
     1973689.385      132752.614
#Sta/Elev= 30
       0 2122.69      10 2120.16      20 2119.84      30 2117.88    79.9 2105.88
   109.8 2096.75   119.8    2096   149.8 2087.48   199.7  2078.2   219.6  2076.4
   299.5 2064.22   383.6    2056   395.6 2055.35   409.1 2055.23     429  2057.5
   458.8 2067.05   488.6 2080.05   498.6 2083.39   508.5 2084.64   528.4 2095.59
   588.1 2131.37     598 2131.61   637.8 2155.62   657.7 2164.03   687.5 2173.31
   697.5 2173.04   747.2 2186.83     777 2192.88     787 2192.62   796.9 2193.72
#Mann= 3 , 0 , 0
       0     .06       0   383.6    .045       0   395.6     .06       0
Bank Sta=383.6,395.6
XS Rating Curve= 0 ,0
Exp/Cntr=0.3,0.1

Type RM Length L Ch R = 1 ,1131.6  ,448.3,434.7,421
XS GIS Cut Line= 3
     1973728.243      133652.401      1973864.65      133368.634
     1974252.515      132911.286
#Sta/Elev= 30
       0 2148.81    29.5 2141.88    49.2 2139.79   137.8 2118.06   147.6 2117.45
   196.8 2103.71     246 2084.82   255.8 2083.82   344.8  2064.9   434.8 2049.93
   436.1 2049.95   448.1 2050.23   504.8 2051.46   524.7 2054.31   554.7 2063.46
   604.7 2086.78   614.7 2088.48   674.6 2128.39   694.6 2147.75   714.6 2162.23
   734.6 2174.92   744.6 2177.93   754.6 2183.84   804.6 2214.79   814.6 2222.76
   844.6  2239.1   854.6 2241.75   864.6 2242.17   904.5 2262.83   914.5 2266.61
#Mann= 3 , 0 , 0
       0     .06       0   436.1    .045       0   448.1     .06       0
Bank Sta=436.1,448.1
XS Rating Curve= 0 ,0
Exp/Cntr=0.3,0.1

Type RM Length L Ch R = 1 ,696.8   ,296.8,287.8,278.9
XS GIS Cut Line= 3
     1974274.077      133821.591     1974272.219       133281.52
     1974308.817      132938.891
#Sta/Elev= 30
       0 2112.69    98.2 2094.27   117.8 2091.91   196.4  2069.2   284.8 2052.74
   353.5 2044.42   408.9 2040.25   412.4 2040.01   420.9 2040.09   461.5 2046.36
   471.3 2052.83   481.2 2061.99     491 2062.86   520.4 2087.94   549.9 2109.46
   579.4 2125.89   589.3 2127.58     609 2135.79   648.4 2158.57   668.1 2172.48
   687.8 2181.77   727.1 2214.26     737 2221.29   746.8 2226.69   766.5 2235.38
   776.4 2238.24   786.2 2239.43   825.6 2253.08   855.1  2256.6   884.6 2258.01
#Mann= 3 , 0 , 0
       0     .06       0   408.9    .045       0   420.9     .06       0
Bank Sta=408.9,420.9
XS Rating Curve= 0 ,0
Exp/Cntr=0.3,0.1

Type RM Length L Ch R = 1 ,408.9   ,227.1,217.9,208.4
XS GIS Cut Line= 3
     1974621.928      133683.602      1974578.25      133538.761
     1974399.779      133008.771
#Sta/Elev= 30
       0 2095.94    37.8 2080.89    66.2 2070.87    75.6 2070.19   132.4 2053.98
   161.3 2048.23   171.3 2048.05   221.2 2040.92   251.2 2033.25   261.1 2032.15
   266.2 2032.18   278.2 2032.42     381 2036.95     391 2040.58   420.9  2072.5
   430.9 2081.51   440.9 2088.66   460.9  2101.2   480.8 2107.75   510.8 2120.77
   550.7 2144.35   560.7 2151.57   570.7 2156.14   580.7 2165.11   590.7 2175.58
   600.7 2184.17   610.6 2192.03   620.6 2198.31   680.6 2213.98   710.5 2223.23
#Mann= 3 , 0 , 0
       0      .1       0   266.2    .045       0   278.2      .1       0
Bank Sta=266.2,278.2
XS Rating Curve= 0 ,0
Exp/Cntr=0.3,0.1

Type RM Length L Ch R = 1 ,190.9   ,168.7,190.7,212.7
XS GIS Cut Line= 4
     1974765.865      133586.419      1974735.79       133486.86
     1974675.815      133272.752     1974448.521      133034.698
#Sta/Elev= 30
       0 2065.71    37.8 2054.39    56.7 2047.76    66.2 2046.87    75.6 2044.88
    85.1 2042.27    94.6 2040.92     162 2036.22   171.7 2036.19   229.7 2032.95
     249 2032.79     307 2033.56     368 2029.39     380 2028.84   386.2 2028.67
   396.2 2028.85   406.1 2031.96   426.1  2048.2     456 2065.22   495.9 2089.78
   505.9 2093.29   515.9 2098.28   535.8 2111.22   555.8  2129.8   585.7 2149.51
   615.6 2170.38   625.6 2176.23   635.5 2181.36   645.5 2184.91   655.5 2189.67
#Mann= 3 , 0 , 0
       0      .1       0     368    .045       0     380      .1       0
Bank Sta=368,380
XS Rating Curve= 0 ,0
Exp/Cntr=0.3,0.1

Chan Stop Cuts=-1
Use User Specified Reach Order=0
Composite Channel Slope=5